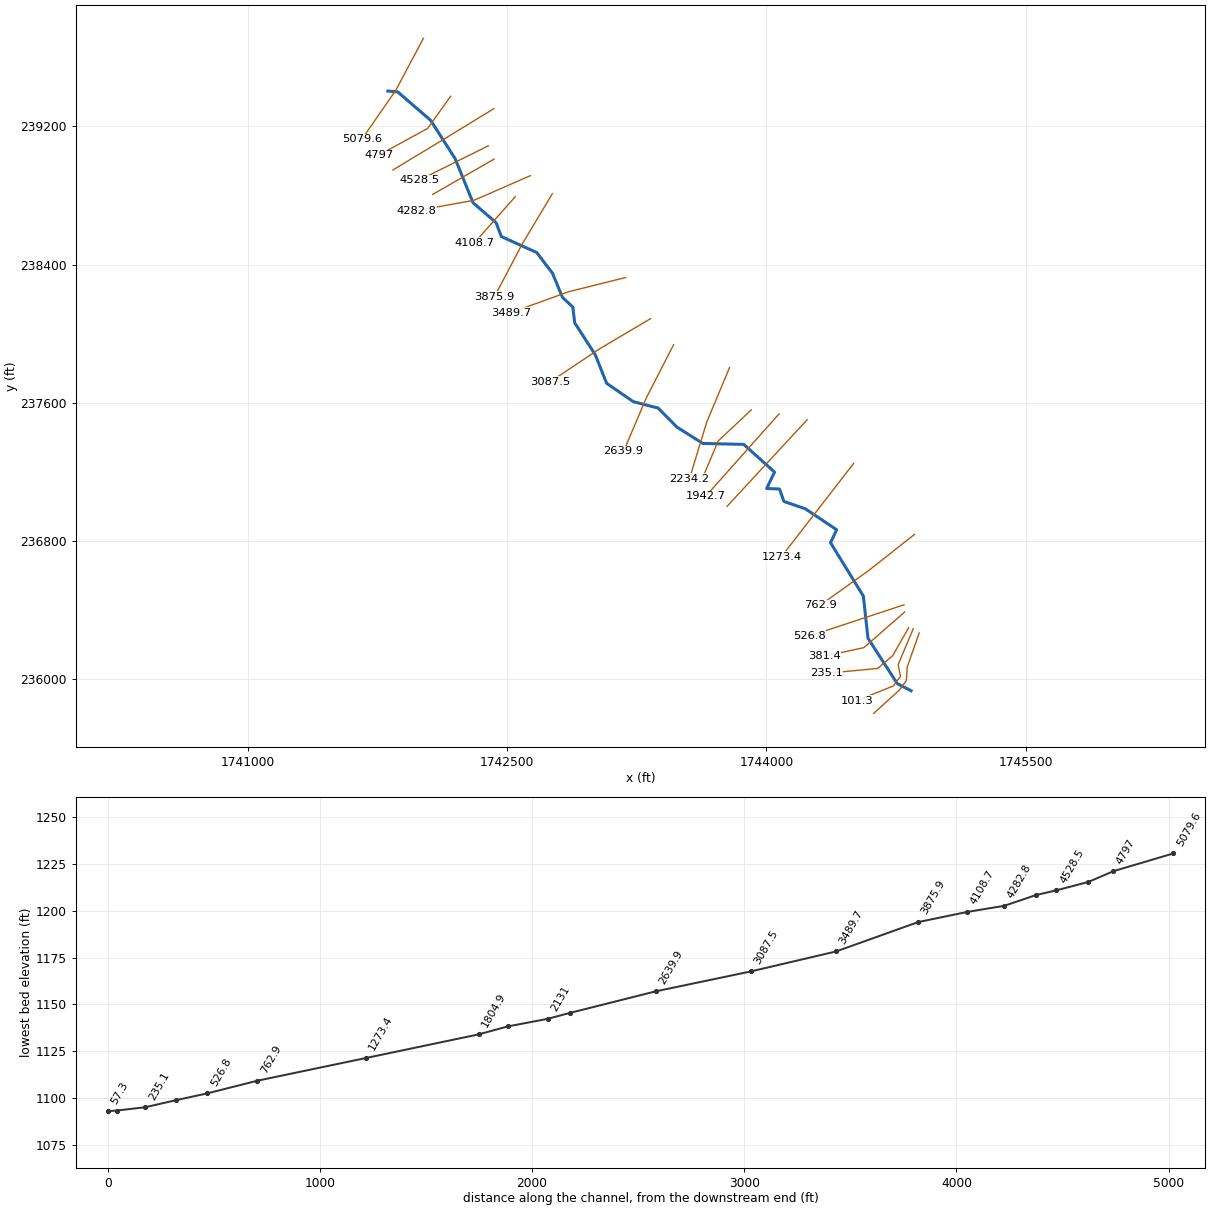
--- ElkTracBr2.prj (project) ---

Proj Title=ElkTracBr2
Current Plan=p01
Default Exp/Contr=0,0
English Units
Geom File=g01
Flow File=f01
Plan File=p01
BEGIN DESCRIPTION:
END DESCRIPTION:
DSS Export Rating Curves= 0
DSS Export Rating Curve Sorted= 0
DSS Export Volume Flow Curves= 0
DXF OffsetX= 0
DXF OffsetY= 0
DXF ScaleX= 0
DXF ScaleY= 0

--- ElkTracBr2.p01 (plan) ---

Plan Title=Floodplain
Program Version=4.00
Geom File=g01
Flow File=f01
K Sum by GR=0
Std Step Tol=0.01
Critical Tol=0.01
Num of Std Step Trials=20
Max Error Tol=0.3
Flow Tol Ratio=0.001
Split Flow NTrial=30
Split Flow Tol=0.02
Split Flow Ratio=0.02
Log Output Level=0
Friction Slope Method=1
Unsteady Friction Slope Method=2
Unsteady Bridges Friction Slope Method=1
Global Log Level=0
CheckData=False
Run HTab=0
Run UNet=0
Run PostProcess=0
UNET Theta=0
UNET Theta Warmup=0
UNET ZTol=0
UNET ZSATol=0
UNET MxIter=0
UNET MaxInSteps=0
UNET DtIC=0
UNET DtMin=0
UNET MaxCRTS=0
UNET WFStab=0
UNET SFStab=0
UNET WFX=0
UNET SFX=0
UNET DSS MLevel=0
UNET DZMax Abort=0
UNET Convert EG Bridges=0
UNET Use Existing IB Tables=0
UNET Froude Limit=0
UNET Froude Power=0
Write IC File=0
Echo Input=False
Echo Output=False
Write Detailed=0

--- ElkTracBr2.f01 (steady flow) ---

Flow Title=NFF Regression Equation
Program Version=4.00
Number of Profiles=1
Profile Names=P100yr
River Rch & RM=ElkTracBr2,Main      ,5079.6
671.6233
River Rch & RM=ElkTracBr2,Main      ,3489.7
737.5349
River Rch & RM=ElkTracBr2,Main      ,381.4
797.9480
Boundary for River Rch & Prof#=ElkTracBr2,Main      ,1
Up Type=0
Dn Type=3
Dn Slope=0.012565

--- ElkTracBr2.g01 (geometry) ---

Geom Title=USGS 10m DEM
Program Version=4.00

River Reach=ElkTracBr2      ,Main
Reach XY= 30
     1741811.176      239405.043     1741868.229      239400.586
     1742059.053       239235.26     1742200.056      239014.061
     1742304.142      238757.858     1742436.967      238642.862
     1742467.415      238562.389     1742671.982       238469.66
     1742763.234      238349.579     1742821.177      238209.623
     1742880.904      238153.462     1742891.601      238062.535
     1743010.162      237878.007     1743076.129      237712.199
     1743231.239      237605.227      1743373.87      237568.678
     1743482.625      237458.139     1743632.387      237363.646
     1743868.879      237358.074     1744046.906      237197.839
     1744001.443      237102.455     1744075.432       237099.78
     1744101.284      237027.574     1744225.194      236984.785
     1744406.157      236863.549     1744370.499      236788.668
     1744560.376      236479.338     1744587.119      236235.084
     1744756.492      235972.109     1744836.516       235930.83

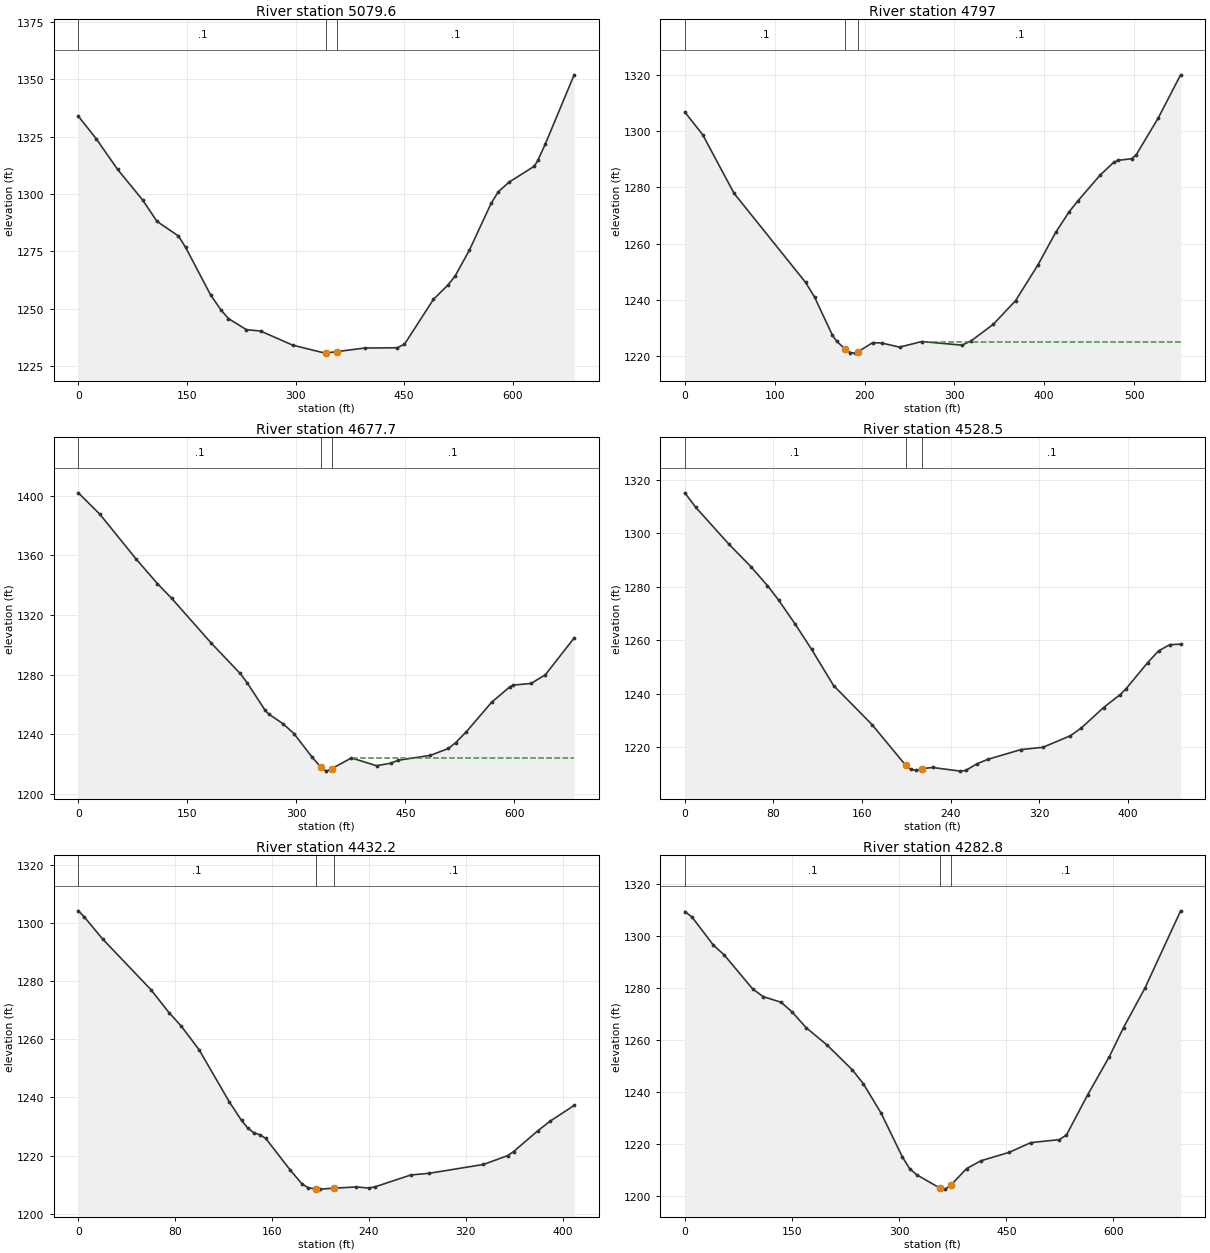
Type RM Length L Ch R = 1 ,5079.6  ,284.2,282.6,283.2
XS GIS Cut Line= 3
     1742016.946      239710.549     1741857.259      239409.542
     1741661.486      239126.534
#Sta/Elev= 30
       0 1333.84    24.7 1324.03    54.3 1310.64    88.9 1297.33   108.6 1288.05
   138.3 1281.67   148.2 1276.71   182.7 1256.02   197.5 1249.27   207.4  1245.7
   232.1 1240.88   251.8 1240.26   296.3 1234.12   340.7 1230.66   342.6 1230.72
   357.6 1231.34   395.6 1232.88   440.5    1233   450.5 1234.52   490.4 1254.02
   510.3 1260.25   520.3 1264.14   540.2 1275.53   570.2  1295.9   580.1 1300.92
   595.1 1305.15     630 1312.09     635 1314.76     645 1321.71   684.9 1351.86
#Mann= 3 , 0 , 0
       0      .1       0   342.6    .045       0   357.6      .1       0
Bank Sta=342.6,357.6
XS Rating Curve= 0 ,0
Exp/Cntr=0.3,0.1

Type RM Length L Ch R = 1 ,4797    ,128.7,119.3,109.9
XS GIS Cut Line= 3
     1742174.544      239374.906     1742041.416      239188.527
     1741758.216      239033.614
#Sta/Elev= 30
       0 1306.75    19.9 1298.72    54.8 1277.91   134.4 1246.28   144.4 1241.08
   164.3  1227.5   169.3 1225.31   177.8 1222.79   184.2 1221.36   189.2 1221.17
   192.8 1221.66   209.1 1224.89   219.1 1224.77     239  1223.3   263.8 1225.28
   308.5    1224   318.4 1225.47   343.3 1231.39   368.1  1239.8   392.9 1252.43
   412.8 1264.05   427.7 1271.33   437.6 1275.28   462.4 1284.43   477.4 1288.91
   482.3  1289.6   497.2 1290.18   502.2 1291.48     527 1304.71   551.8 1319.96
#Mann= 3 , 0 , 0
       0      .1       0   177.8    .045       0   192.8      .1       0
#XS Ineff= 2 , 0
                          266.18         1225.28
Permanent Ineff=
       F       F
Bank Sta=177.8,192.8
XS Rating Curve= 0 ,0
Exp/Cntr=0.3,0.1

Type RM Length L Ch R = 1 ,4677.7  ,151.1,149.2,147.3
XS GIS Cut Line= 3
     1742423.931      239302.986     1742132.839      239124.789
     1741840.995      238948.029
#Sta/Elev= 30
       0 1402.02    29.7 1387.64    79.1 1357.88   108.8 1341.18   128.6 1331.18
     183 1301.22   222.6 1280.96   232.5 1274.58   257.2  1256.1   262.2 1253.62
     282 1247.07   296.8 1240.55   321.5 1224.94   333.8 1218.05   341.3 1215.38
   348.8 1216.99   375.9 1224.24   410.5    1219   430.3 1220.74   440.2 1222.65
   484.7 1225.97   509.4 1230.57   519.3 1234.44   534.2 1241.82   568.8 1261.53
   593.5 1271.73   598.4 1273.05   623.2 1274.19   642.9 1280.02   682.5 1304.69
#Mann= 3 , 0 , 0
       0      .1       0   333.8    .045       0   348.8      .1       0
#XS Ineff= 2 , 0
                          376.34         1224.22
Permanent Ineff=
       F       F
Bank Sta=333.8,348.8
XS Rating Curve= 0 ,0
Exp/Cntr=0.3,0.1

Type RM Length L Ch R = 1 ,4528.5  ,95,96.3,98.1
XS GIS Cut Line= 2
      1742392.39      239088.075     1741991.795      238888.383
#Sta/Elev= 30
       0 1315.15      10 1309.67    39.8 1295.94    59.7  1287.5    74.6 1280.43
    84.6 1275.05    99.5 1266.09   114.4  1256.6   134.3    1243   169.1 1228.35
   199.3 1213.19   203.9 1211.59   208.9 1211.21   214.3 1211.92   223.8 1212.32
   248.7 1210.96   253.6  1211.2   263.6 1213.68   273.5 1215.37   303.4 1219.02
   323.3 1219.89   348.1  1224.2   358.1 1227.17     378 1234.75   392.9 1239.58
   397.9 1241.59   417.8 1251.57   427.7 1255.97   437.7 1258.29   447.6  1258.5
#Mann= 3 , 0 , 0
       0      .1       0   199.3    .045       0   214.3      .1       0
Bank Sta=199.3,214.3
XS Rating Curve= 0 ,0
Exp/Cntr=0.3,0.1

Type RM Length L Ch R = 1 ,4432.2  ,154.5,149.3,141
XS GIS Cut Line= 2
     1742425.067      239010.619     1742070.462      238806.086
#Sta/Elev= 30
       0 1304.28       5 1302.14      20 1294.61    59.9 1277.14    74.9 1269.21
    84.9 1264.62    99.8 1256.38   124.8 1238.38   134.8 1232.07   139.8 1229.52
   144.8 1227.89   149.8 1227.16   154.8 1225.87   174.7 1215.14   184.7 1210.19
   189.7 1208.94   196.1 1208.45   199.7 1208.43   211.1 1208.75   229.6 1209.18
   239.6 1208.82   244.6 1209.17   274.6 1213.31   289.6 1213.88   334.5 1216.92
   354.4 1219.96   359.4 1221.36   379.4 1228.54   389.4 1231.79   409.4 1237.26
#Mann= 3 , 0 , 0
       0      .1       0   196.1    .045       0   211.1      .1       0
Bank Sta=196.1,211.1
XS Rating Curve= 0 ,0
Exp/Cntr=0.3,0.1

Type RM Length L Ch R = 1 ,4282.8  ,161.8,174.2,189.4
XS GIS Cut Line= 3
     1742635.117      238914.705     1742310.341      238772.579
      1741976.29      238711.659
#Sta/Elev= 30
       0 1309.58      10  1307.5      40 1296.65    54.9 1292.96    94.9 1279.81
   109.8 1276.81   134.8 1274.65   149.8 1271.03   169.8 1264.89   199.7 1258.05
   234.7 1248.57   249.7 1243.36   274.6 1232.06   304.6 1215.08   314.6 1210.63
   324.6 1208.23   357.8 1202.98   364.5 1202.69   372.8 1204.35   394.5 1210.59
   414.4  1213.6   454.4 1216.88   484.3 1220.59   524.3 1221.75   534.3 1223.56
   564.2 1239.12   594.2 1253.65   614.2 1264.92   644.1 1280.08   694.1 1309.86
#Mann= 3 , 0 , 0
       0      .1       0   357.8    .045       0   372.8      .1       0
Bank Sta=357.8,372.8
XS Rating Curve= 0 ,0
Exp/Cntr=0.3,0.1

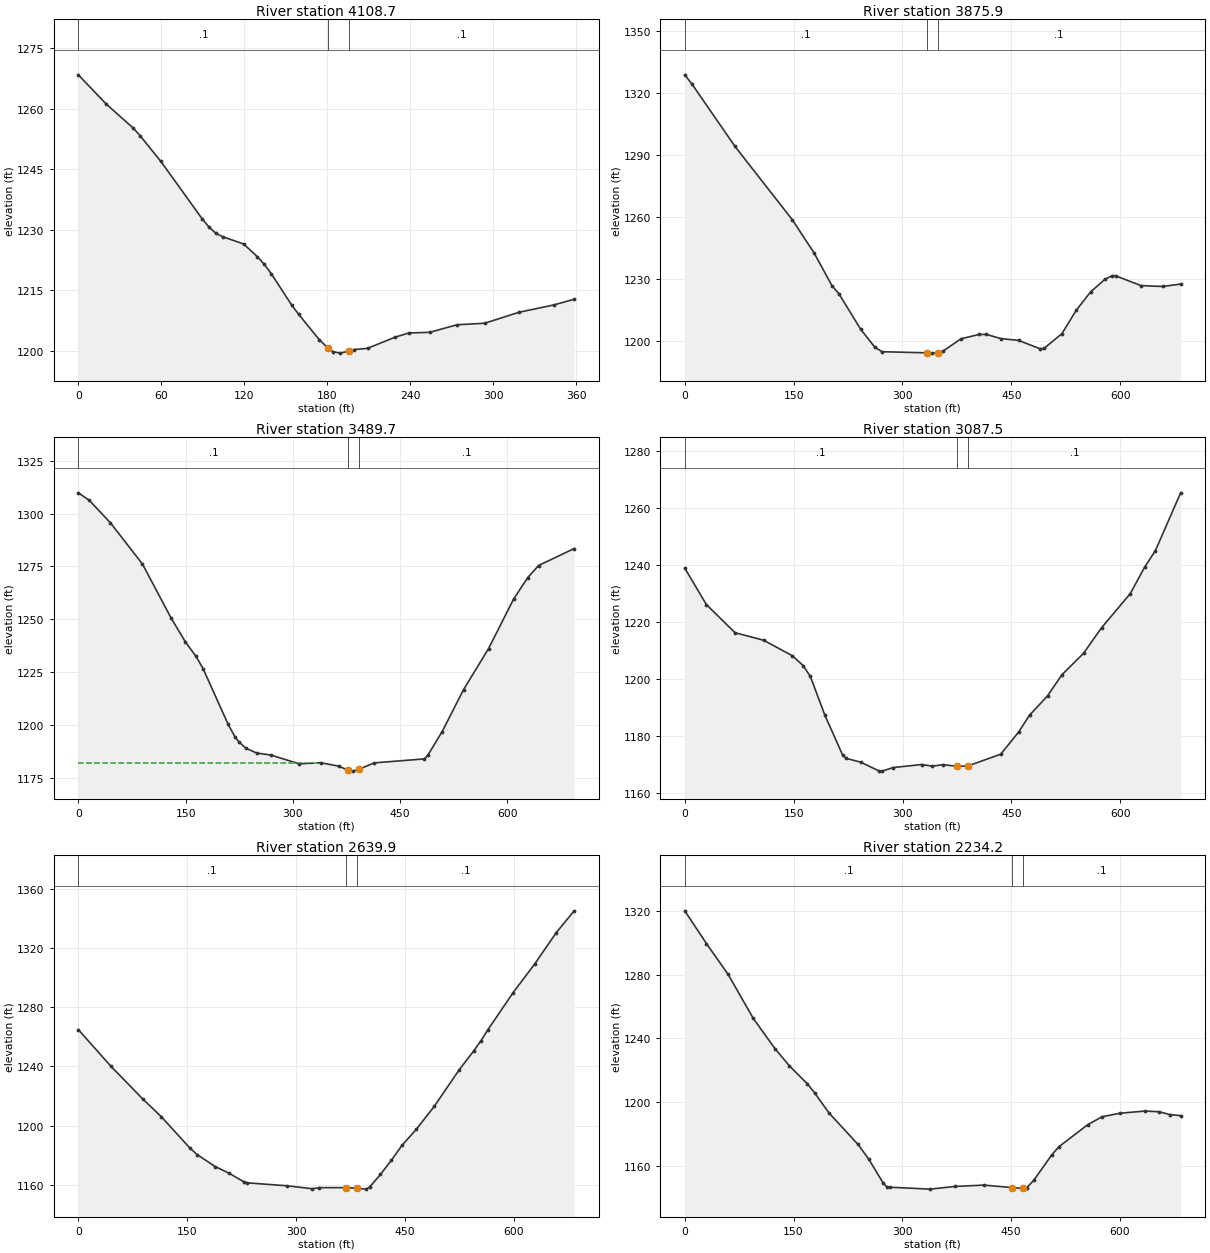
Type RM Length L Ch R = 1 ,4108.7  ,227.4,232.7,238.4
XS GIS Cut Line= 2
     1742548.513      238793.983     1742311.303      238525.306
#Sta/Elev= 30
       0 1268.37    19.9 1261.22    39.8 1255.14    44.8 1253.23    59.7  1246.9
    89.6 1232.66    94.6  1230.6    99.6 1229.07   104.5 1228.24   119.5 1226.47
   129.4 1223.31   134.4 1221.43   139.4 1219.14   154.3 1211.29   159.3 1209.03
   174.2 1202.74   180.8 1200.59   184.2 1199.78   189.2 1199.43   195.8 1199.94
   199.1  1200.3   209.1 1200.62     229 1203.39   238.9 1204.42   253.9 1204.58
   273.8 1206.46   293.7 1206.83   318.6 1209.56   343.5 1211.35   358.4 1212.78
#Mann= 3 , 0 , 0
       0      .1       0   180.8    .045       0   195.8      .1       0
Bank Sta=180.8,195.8
XS Rating Curve= 0 ,0
Exp/Cntr=0.3,0.1

Type RM Length L Ch R = 1 ,3875.9  ,401.8,386.3,369.5
XS GIS Cut Line= 3
     1742762.346      238810.205     1742587.216      238517.534
     1742428.342      238214.408
#Sta/Elev= 30
       0 1328.87     9.9 1324.37    69.2 1294.15   148.3 1258.54     178 1242.64
   202.7 1226.74   212.6 1222.61   242.2 1205.63     262 1196.77   271.9 1194.64
   333.6 1194.11   341.1 1193.96   348.6 1194.08     356 1194.97   380.8 1200.94
   405.6    1203   415.5 1203.05   435.3 1201.02   460.1 1200.12   489.9 1196.04
   494.8 1196.21   519.6 1203.34   539.5 1214.77   559.3 1223.66   579.2  1229.8
   589.1 1231.54     594 1231.39   628.7  1226.7   658.5 1226.26   683.3 1227.44
#Mann= 3 , 0 , 0
       0      .1       0   333.6    .045       0   348.6      .1       0
Bank Sta=333.6,348.6
XS Rating Curve= 0 ,0
Exp/Cntr=0.3,0.1

Type RM Length L Ch R = 1 ,3489.7  ,396.8,402.2,407.5
XS GIS Cut Line= 3
     1743185.291      238324.645     1742856.465      238242.437
     1742523.356       238121.73
#Sta/Elev= 30
       0 1309.77      15 1306.34    44.9  1295.6    89.7  1276.1   129.6 1250.69
   149.5 1239.43   164.5 1232.55   174.5 1226.66   209.4 1200.44   219.3  1194.3
   224.3 1192.17   234.3 1189.12   249.2 1186.86   269.2 1185.89     309 1181.72
     339 1182.27   363.9 1180.65   377.3 1178.74   383.9  1178.3   392.3 1179.18
   413.8  1182.2   483.7 1184.07   488.6 1185.77   508.6 1196.94   538.6 1216.84
   573.5 1236.17   608.4  1259.5   628.4 1269.76   643.4 1275.42   693.2 1283.45
#Mann= 3 , 0 , 0
       0      .1       0   377.3    .045       0   392.3      .1       0
#XS Ineff= 2 , 0
          334.36 1182.32
Permanent Ineff=
       F       F
Bank Sta=377.3,392.3
XS Rating Curve= 0 ,0
Exp/Cntr=0.3,0.1

Type RM Length L Ch R = 1 ,3087.5  ,434.1,447.6,461.1
XS GIS Cut Line= 3
     1743329.703      238086.163     1743036.205      237912.306
     1742751.996      237722.139
#Sta/Elev= 30
       0 1238.81    29.7 1226.07    69.2 1216.18   108.8 1213.52   148.3 1208.08
   163.2 1204.61     173 1200.84   192.8 1187.36   217.5 1173.23   222.5 1172.09
   242.2 1170.77     267 1167.76   271.9 1167.62   286.7 1168.86   326.3 1169.94
   341.1 1169.37     356 1169.88   375.2  1169.3   390.2 1169.46   435.3 1173.56
   460.1 1181.39   474.9 1187.22   499.7    1194   519.5  1201.4   549.3 1208.94
   574.1 1217.89   613.7 1229.89   633.5 1239.15   648.4    1245   683.1 1265.25
#Mann= 3 , 0 , 0
       0      .1       0   375.2    .045       0   390.2      .1       0
Bank Sta=375.2,390.2
XS Rating Curve= 0 ,0
Exp/Cntr=0.3,0.1

Type RM Length L Ch R = 1 ,2639.9  ,401.9,405.7,408.7
XS GIS Cut Line= 3
     1743463.536      237935.486      1743307.43       237630.97
      1743173.78       237317.16
#Sta/Elev= 30
       0 1264.88    44.6 1240.25    89.3 1217.72   114.1  1206.1   153.7 1184.81
   163.7 1180.36   188.5  1172.3   208.3 1167.61   228.1 1161.93   233.1 1161.24
   287.6 1159.26   322.4 1157.26   332.3    1158   369.1    1158   384.1 1157.67
   396.6    1157   401.5 1158.43   416.4 1166.95   431.2 1176.37     446 1186.58
   465.8 1197.48   490.5 1212.97   525.1 1237.89   544.9 1250.46   554.8 1257.34
   564.6  1264.9   599.2 1289.92   628.9 1309.24   658.6 1330.44   683.3 1345.21
#Mann= 3 , 0 , 0
       0      .1       0   369.1    .045       0   384.1      .1       0
Bank Sta=369.1,384.1
XS Rating Curve= 0 ,0
Exp/Cntr=0.3,0.1

Type RM Length L Ch R = 1 ,2234.2  ,118,103.2,99.6
XS GIS Cut Line= 3
     1743786.902      237803.396      1743654.75      237486.532
     1743555.497      237160.416
#Sta/Elev= 30
       0 1320.12    29.8 1299.61    59.7  1280.3    94.5 1252.58   124.4 1233.66
   144.3 1222.83   169.2 1211.51   179.1 1205.92     199 1193.24   238.8 1173.62
   253.8 1164.31   273.7 1149.29   278.6 1146.98   283.6 1146.62   338.3 1145.44
     373 1147.13   412.5 1147.97   451.6 1146.42   466.6 1145.93   471.8 1146.32
   481.6 1150.99   506.4 1166.96   516.2 1172.04   555.8 1185.81   575.5 1190.82
   600.2 1193.07   634.8 1194.43   654.6 1194.02   669.4 1192.23   684.2 1191.57
#Mann= 3 , 0 , 0
       0      .1       0   451.6    .045       0   466.6      .1       0
#XS Ineff= 2 , 0
          412.14 1147.94
Permanent Ineff=
       F       F
Bank Sta=451.6,466.6
XS Rating Curve= 0 ,0
Exp/Cntr=0.3,0.1

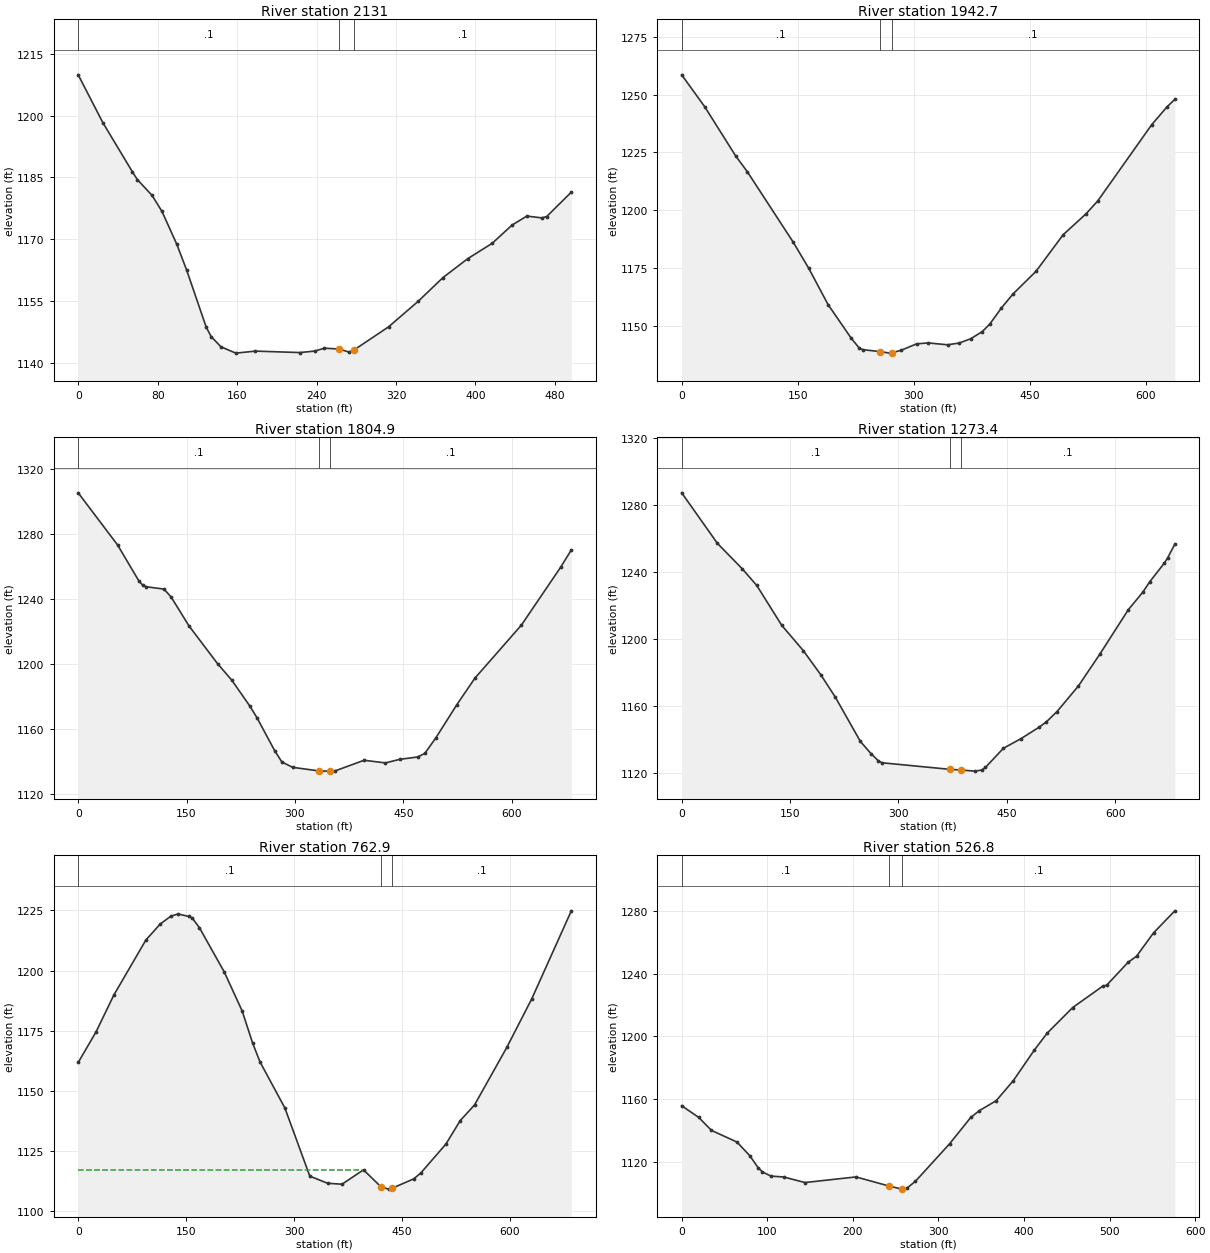
Type RM Length L Ch R = 1 ,2131    ,184,188.3,181.6
XS GIS Cut Line= 3
     1743912.472      237558.312     1743721.251      237377.983
     1743630.482      237162.558
#Sta/Elev= 30
       0 1209.93    24.8 1198.33    54.6 1186.36    59.5  1184.5    74.4 1180.64
    84.3 1176.78    99.2 1168.83   109.1 1162.58   128.9 1148.65   133.9 1146.35
   143.8 1143.86   158.7 1142.33   178.5 1142.82   223.2 1142.47     238 1142.82
     248 1143.53   262.8 1143.33   272.8 1142.58   277.8 1143.09   277.8  1143.1
   312.6 1148.72   342.4 1154.92   367.3 1160.67   392.2 1165.26     417 1169.02
   436.9 1173.43   451.8 1175.62   466.8 1175.18   471.7 1175.49   496.6 1181.43
#Mann= 3 , 0 , 0
       0      .1       0   262.8    .045       0   277.8      .1       0
Bank Sta=262.8,277.8
XS Rating Curve= 0 ,0
Exp/Cntr=0.3,0.1

Type RM Length L Ch R = 1 ,1942.7  ,138.2,137.8,137.4
XS GIS Cut Line= 2
     1744073.436      237535.317     1743649.846      237058.476
#Sta/Elev= 30
       0  1258.5    29.9 1244.65    69.8 1223.47    84.7 1216.73   144.5 1186.07
   164.4 1174.86   189.4 1159.19   219.2 1144.73   229.2 1140.62   234.2 1139.75
   256.5 1138.93   269.1 1138.26   271.5 1138.37     284 1139.52     304 1142.28
   318.9 1142.67   343.8 1141.86   358.8 1142.61   373.7 1144.46   388.7 1147.54
   398.6 1150.86   413.6 1157.81   428.5 1163.82   458.4 1173.66   493.3 1189.39
   523.2 1198.52   538.2 1204.05   607.9 1236.96   627.8  1244.7   637.8 1247.92
#Mann= 3 , 0 , 0
       0      .1       0   256.5    .045       0   271.5      .1       0
Bank Sta=256.5,271.5
XS Rating Curve= 0 ,0
Exp/Cntr=0.3,0.1

Type RM Length L Ch R = 1 ,1804.9  ,509,531.5,533.8
XS GIS Cut Line= 3
      1744235.22      237500.451     1744003.758      237249.699
     1743772.295      236998.947
#Sta/Elev= 30
       0  1305.6    54.4 1273.52    84.1  1251.2      89  1248.8      94 1247.71
   118.7 1246.24   128.6 1241.37   153.3 1223.57   192.9 1200.26   212.7 1190.01
   237.4 1174.22   247.3 1167.04     272 1146.57   281.9 1139.66   296.7 1136.35
   333.8 1134.09   336.3    1134   348.8 1134.09   356.1 1134.23   395.6  1140.7
   425.3 1139.07   445.1 1141.27   469.8 1142.72   479.7 1144.92   494.6 1154.26
   524.2 1175.05     549  1191.3   613.3 1223.98   667.7  1259.7   682.5 1270.39
#Mann= 3 , 0 , 0
       0      .1       0   333.8    .045       0   348.8      .1       0
Bank Sta=333.8,348.8
XS Rating Curve= 0 ,0
Exp/Cntr=0.3,0.1

Type RM Length L Ch R = 1 ,1273.4  ,519,510.5,504.8
XS GIS Cut Line= 3
     1744504.677      237248.373      1744295.99      236978.368
     1744087.367      236708.319
#Sta/Elev= 30
       0 1287.54    49.5 1257.34    84.1 1242.04   103.9 1232.24   138.5  1208.4
   168.2 1193.39   192.9 1178.67   212.7  1165.5   247.3  1139.1   262.1 1131.77
     272 1127.62     277 1126.37   371.5 1122.42   386.5 1122.05   405.6 1121.37
   415.4 1122.02   420.4 1123.56   445.1 1134.97   469.8 1140.81   494.6 1147.58
   504.5 1150.71   519.3 1156.86     549 1172.18   578.6 1191.14   618.2 1217.79
     638 1228.11   647.9  1234.5   667.7 1245.41   672.6 1248.75   682.5 1256.86
#Mann= 3 , 0 , 0
       0      .1       0   371.5    .045       0   386.5      .1       0
Bank Sta=371.5,386.5
XS Rating Curve= 0 ,0
Exp/Cntr=0.3,0.1

Type RM Length L Ch R = 1 ,762.9   ,243,236.1,229
XS GIS Cut Line= 3
     1744856.753      236837.054     1744588.648      236625.225
     1744309.215      236425.295
#Sta/Elev= 30
       0 1161.87    24.8 1174.58    49.5 1189.86    94.1 1212.74   113.9 1219.35
   128.8 1222.63   138.7 1223.55   153.5 1222.53   158.5 1221.88   168.4 1217.87
     203 1199.45   227.8 1183.31   242.6 1169.78   252.6 1162.16   287.2 1142.99
   321.9 1114.66   346.7 1111.71   366.6 1111.32   396.5 1117.29   420.8 1110.23
   431.3 1109.28   435.8  1109.6   466.2 1113.52   476.1 1115.97     511 1127.99
   530.9 1137.74   550.8 1144.24   595.6 1168.11   630.5 1188.42   685.3 1224.85
#Mann= 3 , 0 , 0
       0      .1       0   420.8    .045       0   435.8      .1       0
#XS Ineff= 2 , 0
          396.19 1117.36
Permanent Ineff=
       F       F
Bank Sta=420.8,435.8
XS Rating Curve= 0 ,0
Exp/Cntr=0.3,0.1

Type RM Length L Ch R = 1 ,526.8   ,136.8,145.4,154
XS GIS Cut Line= 2
     1744795.427      236428.722     1744248.335      236247.699
#Sta/Elev= 30
       0 1155.78    19.9 1148.32    34.8 1140.03    64.6 1132.58    79.5 1123.92
    89.4 1116.16    94.4  1113.5   104.3 1110.83   119.2 1110.26   144.1 1106.72
   203.7 1110.31   242.4 1104.46   257.4 1102.54   258.3 1102.51   263.3 1103.16
   273.2 1107.54     313 1131.42   337.8 1148.29   347.7 1152.59   367.6 1159.02
   387.5 1171.76   412.3 1191.48   427.2 1202.18     457 1218.52   491.8 1232.04
   496.8 1232.85   521.6 1247.34   531.6  1251.3   551.4 1266.17   576.3 1280.27
#Mann= 3 , 0 , 0
       0      .1       0   242.4    .045       0   257.4      .1       0
Bank Sta=242.4,257.4
XS Rating Curve= 0 ,0
Exp/Cntr=0.3,0.1

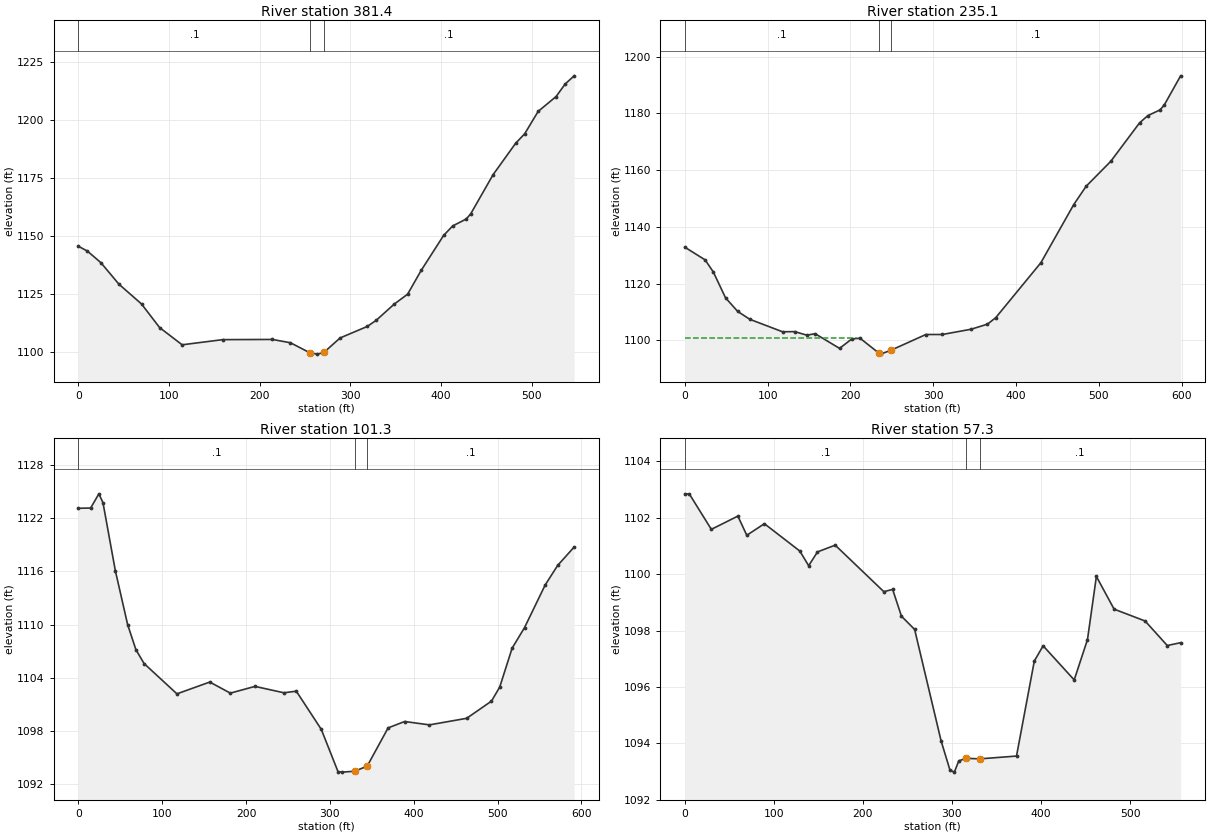
Type RM Length L Ch R = 1 ,381.4   ,146.7,146.4,146.1
XS GIS Cut Line= 3
      1744799.45      236387.154     1744563.449      236180.654
     1744335.494       236131.04
#Sta/Elev= 30
       0 1145.57      10 1143.46    24.9 1138.46    44.8 1129.16    69.7 1120.62
    89.6 1110.44   114.5 1102.98   159.3 1105.21     214 1105.29     234 1103.86
   255.8 1099.44   263.8 1098.95   270.8 1099.66   288.7 1105.93   318.6 1110.89
   328.5 1113.53   348.3 1120.52   363.2 1124.84   378.1 1135.08   402.9 1150.22
   412.9 1154.33   427.8 1157.31   432.7 1159.49   457.5 1176.49   482.4 1190.06
   492.3 1194.12   507.2 1203.82     527 1210.24     537 1215.66   546.9 1219.18
#Mann= 3 , 0 , 0
       0      .1       0   255.8    .045       0   270.8      .1       0
#XS Ineff= 2 , 0
           216.3 1105.12
Permanent Ineff=
       F       F
Bank Sta=255.8,270.8
XS Rating Curve= 0 ,0
Exp/Cntr=0.3,0.1

Type RM Length L Ch R = 1 ,235.1   ,128.4,133.7,139
XS GIS Cut Line= 4
     1744822.245      236295.972     1744729.722      236133.722
     1744642.563      236059.972     1744346.222      236031.812
#Sta/Elev= 30
       0 1132.82    24.6 1128.32    34.4 1124.08    49.2 1114.96    63.9 1110.16
    78.6 1107.38     118    1103   132.7 1103.05   147.5 1101.79   157.3 1102.33
   186.8 1097.15   201.7 1100.48   211.6 1100.72   234.5 1095.44   236.4 1095.12
   249.5 1096.57     291 1102.03   310.9 1102.04   345.6 1103.89   365.4 1105.68
   375.4 1107.97   429.9 1127.34   469.6 1147.84   484.5 1154.27   514.3 1163.08
     549 1176.61   558.9 1179.16   573.8 1181.21   578.8  1182.9   598.6  1193.2
#Mann= 3 , 0 , 0
       0      .1       0   234.5    .045       0   249.5      .1       0
#XS Ineff= 2 , 0
          208.33  1100.9
Permanent Ineff=
       F       F
Bank Sta=234.5,249.5
XS Rating Curve= 0 ,0
Exp/Cntr=0.3,0.1

Type RM Length L Ch R = 1 ,101.3   ,44,44,44
XS GIS Cut Line= 5
     1744849.063      236290.608     1744761.904      236082.767
     1744775.077      236014.699     1744733.606      235958.525
     1744523.222      235873.585
#Sta/Elev= 30
       0 1123.13    14.7 1123.16    24.5 1124.76    29.4 1123.76    44.1 1116.11
    58.8 1110.01    68.6  1107.2    78.4 1105.62   117.6  1102.2   156.8 1103.53
   181.3 1102.28   210.7 1103.04   245.2 1102.32     260  1102.5   289.8 1098.19
   309.7 1093.43   314.7 1093.37   329.5 1093.47   344.5 1094.04   369.5 1098.36
   389.2 1099.08   418.8  1098.7   463.2 1099.44   492.8 1101.38   502.6 1102.96
   517.4 1107.35   532.2 1109.67   556.9 1114.49   571.7 1116.68   591.4 1118.76
#Mann= 3 , 0 , 0
       0      .1       0   329.5    .045       0   344.5      .1       0
Bank Sta=329.5,344.5
XS Rating Curve= 0 ,0
Exp/Cntr=0.3,0.1

Type RM Length L Ch R = 1 ,57.3    ,55.5,57.3,59.1
XS GIS Cut Line= 5
      1744883.08      236265.624      1744814.16      236068.673
     1744809.093      235989.714     1744767.623       235933.54
     1744620.127      235799.742
#Sta/Elev= 30
       0 1102.84       5 1102.85    29.8 1101.59    59.6 1102.06    69.6 1101.38
    89.4 1101.79   129.2 1100.82   139.1  1100.3     149 1100.79   168.9 1101.03
   223.5 1099.38   233.4 1099.46   243.3 1098.51   258.1 1098.04   287.8 1094.09
   297.8 1093.05   302.7 1092.98   307.7 1093.38   316.1 1093.47   331.1 1093.45
   372.5 1093.55   392.5 1096.92   402.4 1097.46   437.3 1096.25   452.2 1097.68
   462.2 1099.92   482.1 1098.76   516.9 1098.34   541.8 1097.47   556.8 1097.57
#Mann= 3 , 0 , 0
       0      .1       0   316.1    .045       0   331.1      .1       0
Bank Sta=316.1,331.1
XS Rating Curve= 0 ,0
Exp/Cntr=0.3,0.1

Chan Stop Cuts=-1
Use User Specified Reach Order=0